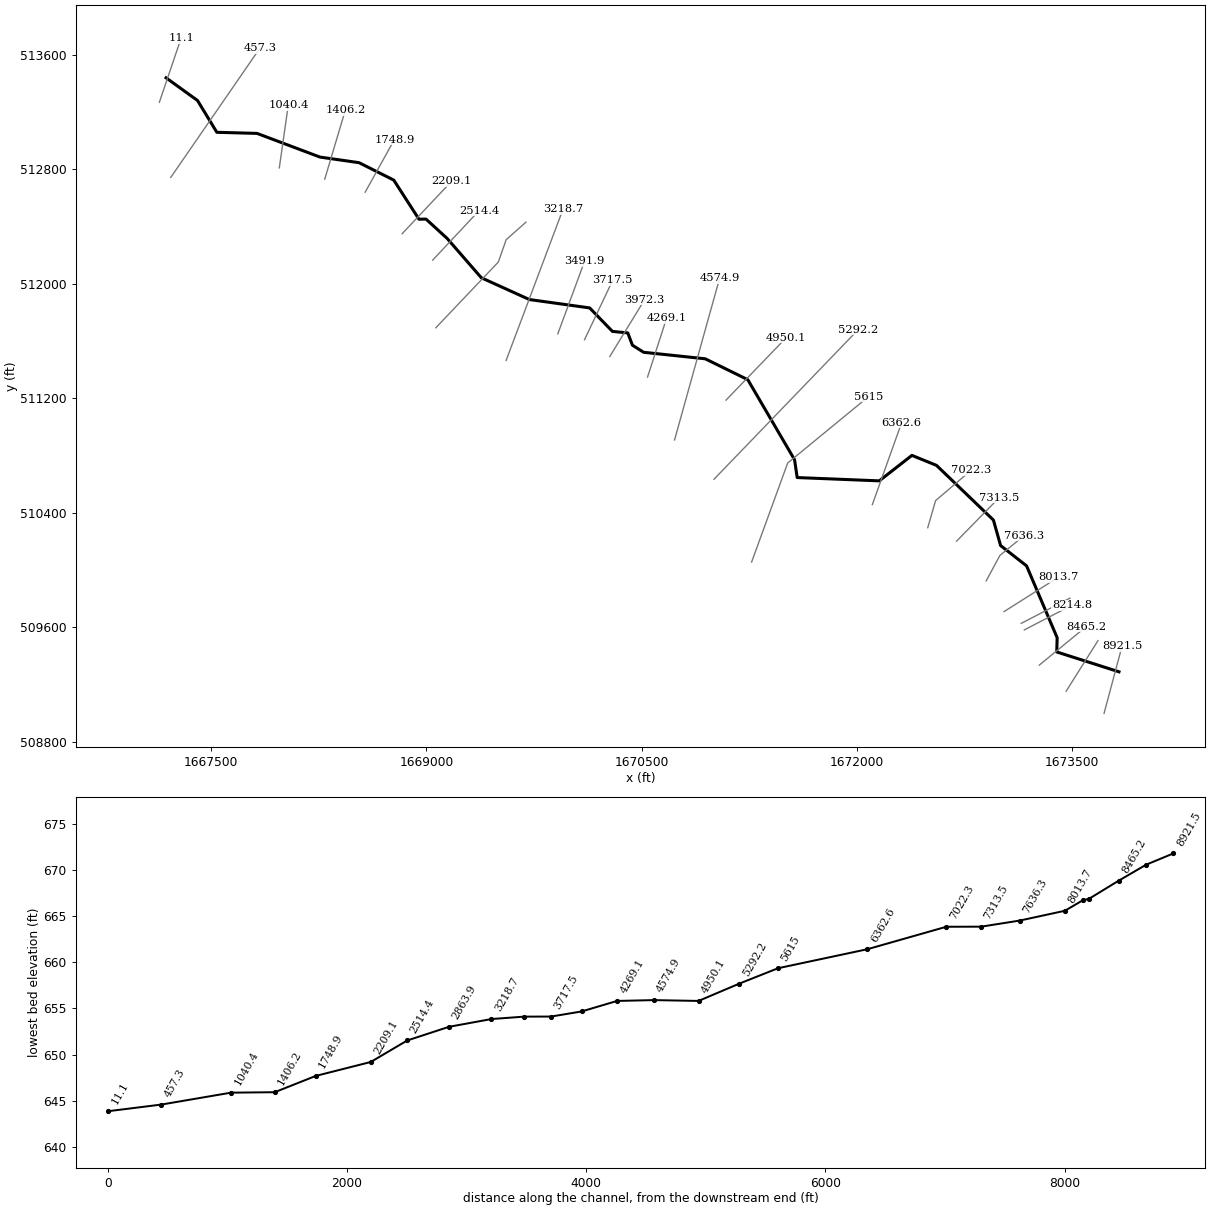
--- CharleyCr.prj (project) ---

Proj Title=CharleyCr
Current Plan=p01
Default Exp/Contr=0,0
English Units
Geom File=g01
Flow File=f01
Plan File=p01
BEGIN DESCRIPTION:
AMEC Environment & Infrastructure, 2013
Projection: NAD 1983 State Plane West Virginia South FIPS 4702 (US Feet)
Vertical Datum: NAVD 1988
END DESCRIPTION:
DSS Export Rating Curves= 0
DSS Export Rating Curve Sorted= 0
DSS Export Volume Flow Curves= 0
DXF OffsetX= 0
DXF OffsetY= 0
DXF ScaleX= 0
DXF ScaleY= 0

--- CharleyCr.p01 (plan) ---

Plan Title=Floodplain
Program Version=4.00
Geom File=g01
Flow File=f01
K Sum by GR=0
Std Step Tol=0.01
Critical Tol=0.01
Num of Std Step Trials=20
Max Error Tol=0.3
Flow Tol Ratio=0.001
Split Flow NTrial=30
Split Flow Tol=0.02
Split Flow Ratio=0.02
Log Output Level=0
Friction Slope Method=1
Unsteady Friction Slope Method=2
Unsteady Bridges Friction Slope Method=1
Global Log Level=0
CheckData=False
Run HTab=0
Run UNet=0
Run PostProcess=0
UNET Theta=0
UNET Theta Warmup=0
UNET ZTol=0
UNET ZSATol=0
UNET MxIter=0
UNET MaxInSteps=0
UNET DtIC=0
UNET DtMin=0
UNET MaxCRTS=0
UNET WFStab=0
UNET SFStab=0
UNET WFX=0
UNET SFX=0
UNET DSS MLevel=0
UNET DZMax Abort=0
UNET Convert EG Bridges=0
UNET Use Existing IB Tables=0
UNET Froude Limit=0
UNET Froude Power=0
Write IC File=0
Echo Input=False
Echo Output=False
Write Detailed=0

--- CharleyCr.f01 (steady flow) ---

Flow Title=USGS Regress. Eqn. (2010) - Western-Plateaus
Program Version=4.00
Number of Profiles=1
Profile Names=P100yr
River Rch & RM=CharleyCr,Main      ,8921.5
     903
River Rch & RM=CharleyCr,Main      ,8214.8
     909
River Rch & RM=CharleyCr,Main      ,7313.5
     930
River Rch & RM=CharleyCr,Main      ,5615
     987
River Rch & RM=CharleyCr,Main      ,5292.2
     992
River Rch & RM=CharleyCr,Main      ,4950.1
    1246
River Rch & RM=CharleyCr,Main      ,4574.9
    1297
River Rch & RM=CharleyCr,Main      ,2863.9
    1320
River Rch & RM=CharleyCr,Main      ,2514.4
    1446
River Rch & RM=CharleyCr,Main      ,1748.9
    1482
River Rch & RM=CharleyCr,Main      ,457.3
    1523
Boundary for River Rch & Prof#=CharleyCr,Main      ,1
Up Type=0
Dn Type=3
Dn Slope=0.001322

--- CharleyCr.g01 (geometry) ---

Geom Title=USGS 3m DEM
Program Version=4.10

River Reach=CharleyCr       ,Main
Reach XY= 30
       1673827.4      509289.582      1673393.73      509428.227
     1673396.492      509527.692     1673183.444      510029.355
     1673002.237        510171.5     1672952.324      510349.451
     1672555.582      510731.358     1672384.228      510801.236
     1672156.797      510623.285     1671584.546      510646.342
     1671566.271      510770.828     1671240.218      511329.973
      1670943.69      511475.806     1670514.088      511521.322
     1670436.311      511570.771     1670403.759      511656.709
     1670296.988      511667.125     1670138.134      511831.188
     1669718.054       511889.71     1669383.034      512041.821
     1669144.265      512317.053     1668997.292      512451.699
     1668948.464      512450.614     1668772.683      512724.052
     1668530.712      512845.579     1668258.505      512884.714
     1667819.915      513050.117     1667539.639      513057.761
     1667405.017      513279.859     1667185.774      513438.303

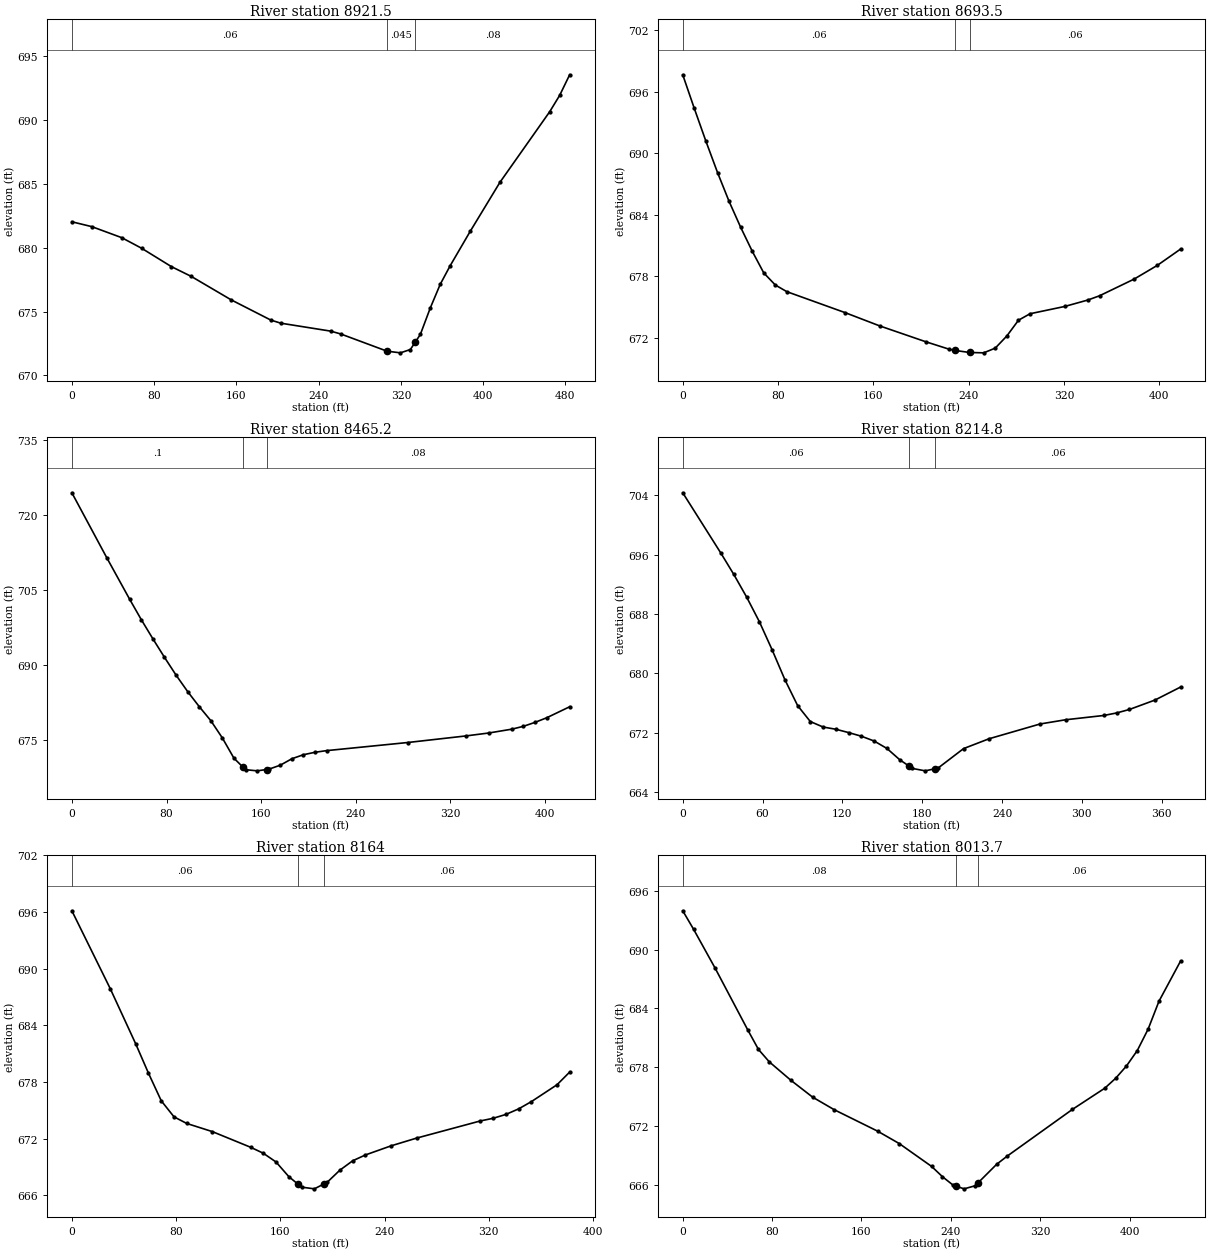
Type RM Length L Ch R = 1 ,8921.5  ,235.2,228,220.1
XS GIS Cut Line= 2
     1673723.444       508999.26      1673848.31      509466.991
#Sta/Elev= 24
       0  682.03    19.4  681.65    48.4  680.79    67.8  679.96    96.8  678.52
   116.2  677.75   154.9  675.92   193.6  674.33   203.3  674.09   251.7  673.47
   261.4  673.25   306.5   671.9   319.5  671.77   329.2  672.03     334 672.614
   338.9  673.21   348.6  675.29   358.2  677.13   367.9  678.59   387.3  681.27
   416.3  685.12   464.8  690.66   474.4  691.93   484.1  693.54
#Mann= 3 , 0 , 0
       0     .06       0   306.5    .045       0     334     .08       0
Bank Sta=306.5,334
XS Rating Curve= 0 ,0
Exp/Cntr=0.3,0.1

Type RM Length L Ch R = 1 ,8693.5  ,236.3,228.3,225.2
XS GIS Cut Line= 2
     1673459.069       509153.83     1673681.272      509507.638
#Sta/Elev= 27
       0  697.65     9.7  694.37    19.4  691.19    29.2  688.12    38.9  685.31
    48.6  682.79    58.3  680.46      68  678.34    77.7  677.16    87.4  676.51
     136  674.48   165.2  673.18     204  671.63   223.4  670.91   228.5 670.785
   240.7 670.585   252.6  670.55   262.3  671.01     272  672.19   281.8  673.73
   291.5  674.36   320.6  675.07   340.1   675.7   349.8  676.11   378.9  677.74
   398.4  679.08   417.8  680.66
#Mann= 3 , 0 , 0
       0     .06       0   228.5    .045       0   240.7     .06       0
Bank Sta=228.5,240.7
XS Rating Curve= 0 ,0
Exp/Cntr=0.3,0.1

Type RM Length L Ch R = 1 ,8465.2  ,255,250.4,237.2
XS GIS Cut Line= 2
     1673271.998      509336.433     1673597.082      509603.676
#Sta/Elev= 30
       0  724.42    29.4  711.48    48.9  703.11    58.7  699.05    68.5  695.22
    78.3  691.52    88.1  687.96    97.9  684.67   107.6  681.69   117.4  678.88
   127.2  675.41     137  671.36   144.6  669.58   146.8  669.06   156.6  668.83
   164.6  669.09   166.4  669.15   176.2  669.96     186  671.25   195.7  672.05
   205.5  672.54   215.3  672.87   283.8  674.49   332.8   675.8   352.3  676.39
   371.9  677.16   381.7  677.73   391.5  678.52   401.3  679.43   420.8  681.64
#Mann= 3 , 0 , 0
       0      .1       0   144.6    .045       0   164.6     .08       0
Bank Sta=144.6,164.6
XS Rating Curve= 0 ,0
Exp/Cntr=0.3,0.1

Type RM Length L Ch R = 1 ,8214.8  ,50.6,50.8,50.6
XS GIS Cut Line= 2
     1673167.761      509582.347     1673499.819      509754.806
#Sta/Elev= 30
       0  704.36    28.8  696.18    38.4  693.34      48   690.3    57.6  686.97
    67.2  683.17    76.8  679.14    86.4  675.64    95.9   673.5   105.5  672.76
   115.1  672.46   124.7  672.01   134.3  671.52   143.9  670.87   153.5  669.87
   163.1  668.35   169.8  667.53   172.7  667.17   182.3  666.85   189.8  667.14
   191.9  667.22   211.1  669.85   230.3  671.18   268.6  673.17   287.8  673.74
   316.6  674.32   326.2  674.66   335.8  675.13     355   676.4   374.2  678.15
#Mann= 3 , 0 , 0
       0     .06       0   169.8    .045       0   189.8     .06       0
Bank Sta=169.8,189.8
XS Rating Curve= 0 ,0
Exp/Cntr=0.3,0.1

Type RM Length L Ch R = 1 ,8164    ,148.2,150.3,152.5
XS GIS Cut Line= 2
     1673146.328       509627.98      1673485.38      509804.073
#Sta/Elev= 29
       0  696.14    29.4  687.91      49  682.05    58.8  678.94    68.6  676.02
    78.4  674.32    88.2  673.62   107.8  672.76   137.2   671.1   146.9  670.47
   156.7  669.54   166.5  667.99   173.5667.1985   176.3  666.88   186.1   666.7
   193.5667.2215   195.9  667.39   205.7  668.68   215.5  669.67   225.3  670.29
   244.9  671.25   264.5  672.07   313.5  673.89   323.3  674.17   333.1  674.58
   342.9  675.17   352.7  675.94   372.3  677.72     382  679.06
#Mann= 3 , 0 , 0
       0     .06       0   173.5    .045       0   193.5     .06       0
Bank Sta=173.5,193.5
XS Rating Curve= 0 ,0
Exp/Cntr=0.3,0.1

Type RM Length L Ch R = 1 ,8013.7  ,374,377.4,379.3
XS GIS Cut Line= 2
     1673026.501      509710.209     1673402.894      509948.798
#Sta/Elev= 28
       0  693.99     9.7   692.1    29.1   688.1    58.1  681.83    67.8  679.81
    77.5  678.54    96.9  676.65   116.2  674.94   135.6  673.65   174.4  671.46
   193.8  670.19   222.8  667.85   232.5   666.8   242.2  665.92   244.2665.8476
   251.9  665.56   261.6  665.87   264.2666.1563     281  668.07   290.6  668.92
   348.8  673.68   377.8  675.85   387.5  676.86   397.2  678.12   406.9   679.7
   416.6  681.89   426.3  684.74   445.6  688.84
#Mann= 3 , 0 , 0
       0     .08       0   244.2    .045       0   264.2     .06       0
Bank Sta=244.2,264.2
XS Rating Curve= 0 ,0
Exp/Cntr=0.3,0.1

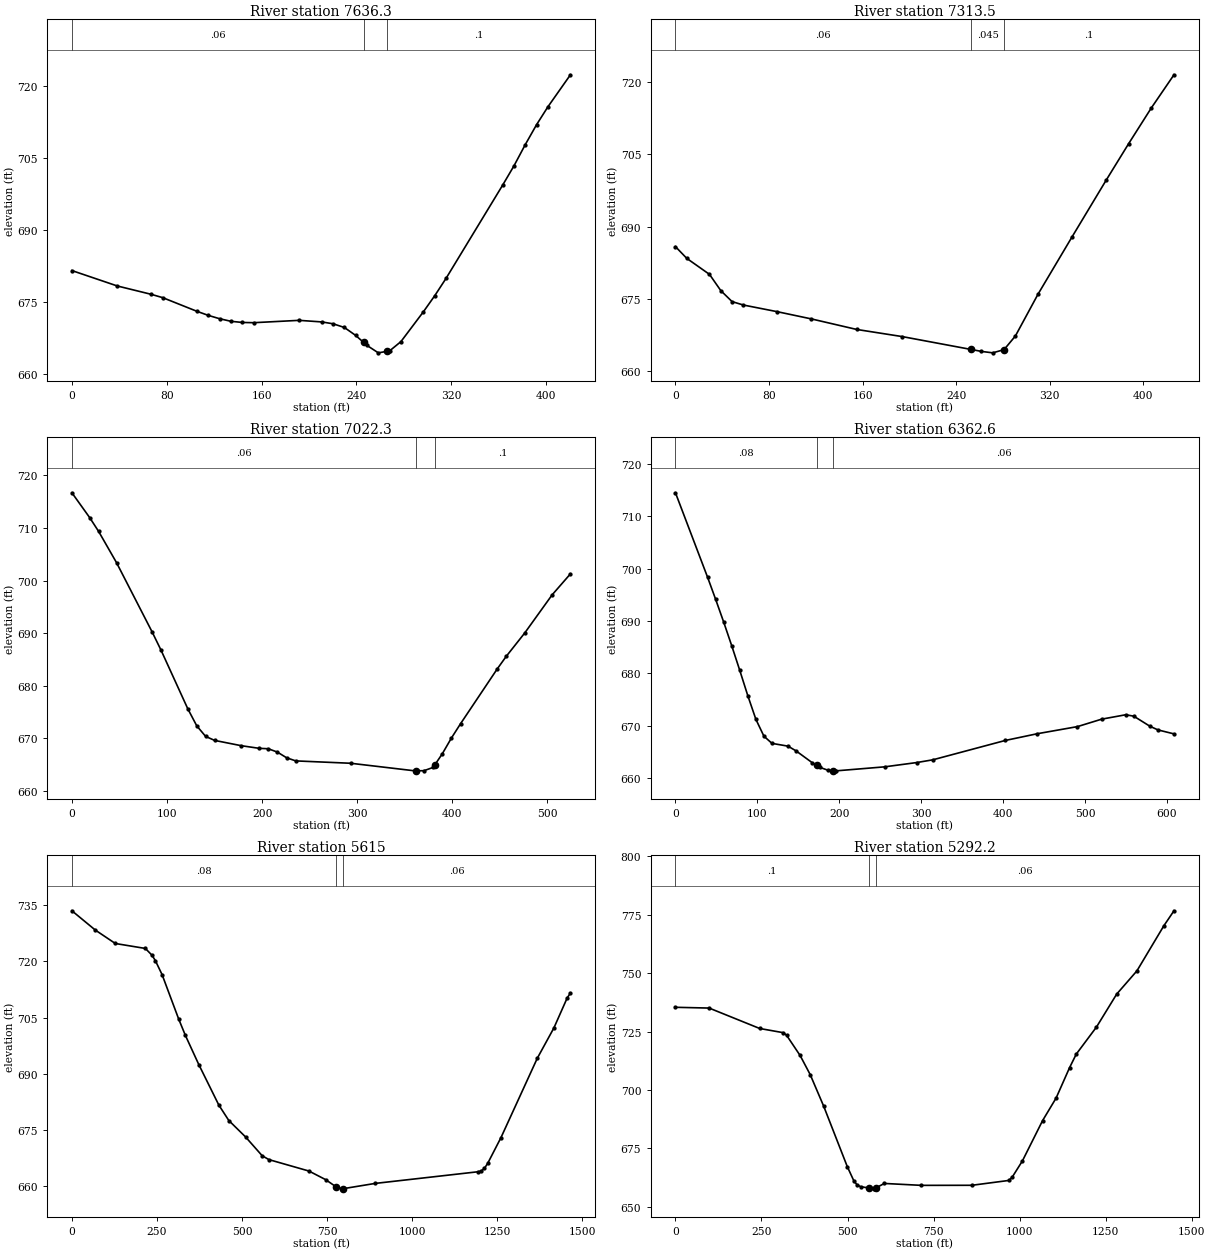
Type RM Length L Ch R = 1 ,7636.3  ,319.4,322.9,326.1
XS GIS Cut Line= 3
     1672901.845      509924.497     1672997.078      510101.822
     1673166.525       510241.12
#Sta/Elev= 30
       0  681.64    38.3  678.43    67.1  676.68    76.7  675.99   105.4  673.16
     115  672.31   124.6  671.61   134.2  671.07   143.8  670.83   153.4  670.78
   191.7  671.27   210.8  670.94   220.4  670.55   229.9  669.78   239.4  668.13
   246.1  666.67     249  666.04   258.5   664.5   266.1  664.82     268   664.9
   277.6  666.84   296.6  673.07   306.2  676.43   315.7  680.03   363.4  699.43
     373  703.47   382.5  707.88     392  712.02   401.6  715.76   420.6  722.43
#Mann= 3 , 0 , 0
       0     .06       0   246.1    .045       0   266.1      .1       0
Bank Sta=246.1,266.1
XS Rating Curve= 0 ,0
Exp/Cntr=0.3,0.1

Type RM Length L Ch R = 1 ,7313.5  ,293.1,291.1,288.7
XS GIS Cut Line= 2
       1672695.5      510202.111     1672993.429      510506.906
#Sta/Elev= 21
       0  685.88     9.7  683.44    29.1  680.12    38.8  676.74    48.4  674.47
    58.1  673.76    87.2  672.37   116.2  670.88     155  668.69   193.7  667.22
   252.8  664.54   261.5  664.14   271.2  663.84   280.9   664.5   290.6  667.33
     310  676.03     339  687.88   368.1  699.62   387.5  707.27   406.8  714.65
   426.2  721.54
#Mann= 3 , 0 , 0
       0     .06       0   252.8    .045       0   280.9      .1       0
Bank Sta=252.8,280.9
XS Rating Curve= 0 ,0
Exp/Cntr=0.3,0.1

Type RM Length L Ch R = 1 ,7022.3  ,648.6,659.7,657.8
XS GIS Cut Line= 3
     1672494.551      510296.038     1672549.179      510485.195
     1672797.947      510697.985
#Sta/Elev= 30
       0   716.7    18.8  711.95    28.1  709.35    46.9  703.42    84.4  690.22
    93.8  686.74   121.9  675.61   131.3  672.38   140.6  670.38     150  669.62
   178.1  668.61   196.9  668.11   206.5  668.03   216.1  667.39   225.8  666.31
   235.4  665.72   293.2  665.27   360.6  663.83   361.5  663.83   370.2  663.86
   379.8  664.48   381.5  664.94   389.4  667.05   399.1  670.08   408.7   672.8
   447.2   683.2   456.8  685.62   476.1  690.03     505   697.3   524.2  701.28
#Mann= 3 , 0 , 0
       0     .06       0   361.5    .045       0   381.5      .1       0
Bank Sta=361.5,381.5
XS Rating Curve= 0 ,0
Exp/Cntr=0.3,0.1

Type RM Length L Ch R = 1 ,6362.6  ,757.6,747.7,745.8
XS GIS Cut Line= 2
     1672108.437      510457.358     1672312.921      511030.584
#Sta/Elev= 30
       0  714.45    39.3   698.3    49.1   694.1    58.9  689.77    68.7  685.26
    78.5  680.57    88.4   675.7    98.2  671.22     108  668.01   117.8  666.64
   137.4  666.11   147.2  665.21   166.9  662.96   172.6  662.42   176.7  662.04
   186.5   661.5   192.6  661.44   196.3   661.4   255.2  662.16   294.5  662.98
   314.1   663.5   402.5  667.19   441.7  668.48   490.8  669.84   520.3  671.26
   549.7   672.1   559.5  671.83   579.2  669.91     589  669.21   608.6  668.45
#Mann= 3 , 0 , 0
       0     .08       0   172.6    .045       0   192.6     .06       0
Bank Sta=172.6,192.6
XS Rating Curve= 0 ,0
Exp/Cntr=0.3,0.1

Type RM Length L Ch R = 1 ,5615    ,318.1,322.8,326.4
XS GIS Cut Line= 3
     1671266.944      510056.145     1671518.349      510747.847
     1672081.431      511211.355
#Sta/Elev= 30
       0  733.53    68.7  728.39   127.6   724.8   215.9  723.48   235.5  721.66
   245.3  720.23     265  716.51     314  704.61   333.6  700.27   372.9  692.51
   431.8   681.7   461.2  677.57   510.3   673.2   559.3  668.17     579  667.14
   696.7  664.09   745.7   661.8   775.8  659.92   794.3  659.34   795.8  659.36
   891.6  660.79    1193  663.89  1202.7  664.08  1212.5   664.8  1222.2  666.15
  1261.1     673    1368   694.2  1416.7  702.27  1455.6  710.24  1465.3   711.6
#Mann= 3 , 0 , 0
       0     .08       0   775.8    .045       0   795.8     .06       0
Bank Sta=775.8,795.8
XS Rating Curve= 0 ,0
Exp/Cntr=0.3,0.1

Type RM Length L Ch R = 1 ,5292.2  ,342,342,341.2
XS GIS Cut Line= 2
       1671004.7       510634.39     1672008.968      511678.458
#Sta/Elev= 30
       0  735.42    97.9  735.09   244.7  726.35   313.2  724.55     323  723.42
   362.2  714.79   391.5  706.62   430.7  693.09   499.2  667.24   518.8  660.97
   528.6  659.29   538.4  658.58   562.3  658.06   577.5  657.68   582.3  658.05
   606.9  659.99   714.5  659.17   861.4   659.2     969  661.28   978.8  662.74
  1008.2  669.63  1066.9  686.91  1106.1  696.54  1145.2  709.55  1164.8  715.39
  1223.5  726.97  1282.3  741.09    1341  751.02  1419.3  770.34  1448.7  776.75
#Mann= 3 , 0 , 0
       0      .1       0   562.3    .045       0   582.3     .06       0
Bank Sta=562.3,582.3
XS Rating Curve= 0 ,0
Exp/Cntr=0.3,0.1

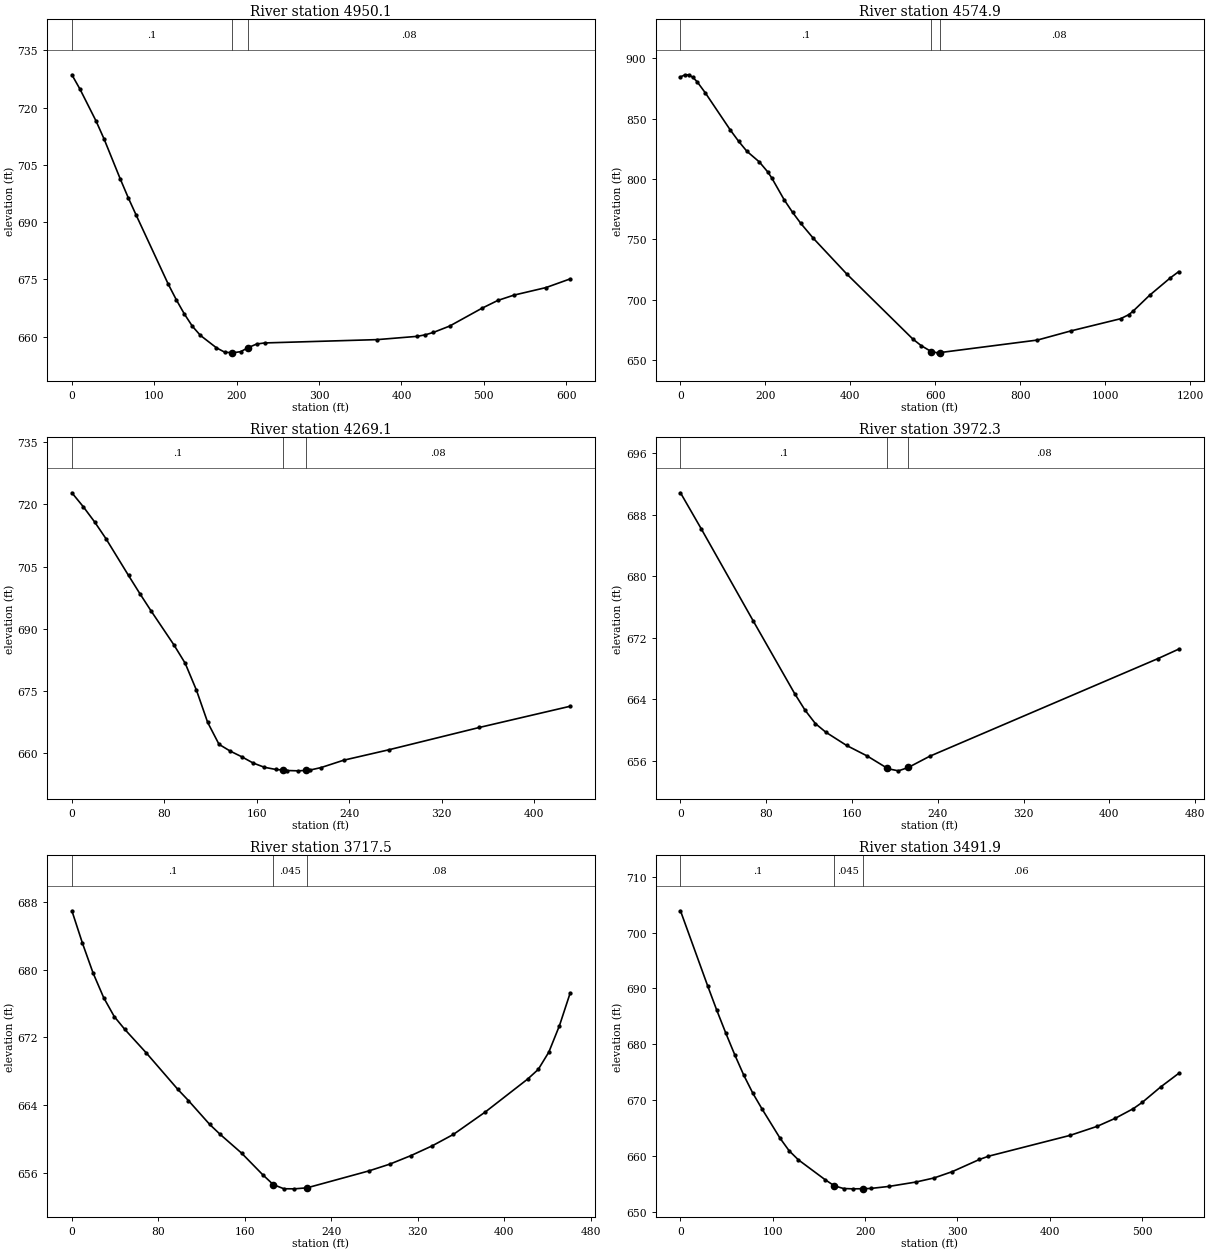
Type RM Length L Ch R = 1 ,4950.1  ,362,375.3,387.9
XS GIS Cut Line= 2
     1671088.512      511187.111     1671507.667      511622.877
#Sta/Elev= 30
       0  728.57     9.8  724.82    29.3  716.48      39   711.8    58.5  701.42
    68.3  696.44      78  691.85     117  673.75   126.8  669.66   136.5  665.97
   146.3  662.74     156  660.36   175.5  657.11   185.3  655.99   194.1  655.82
     195   655.8   204.8  656.11   214.1  657.18   224.3  658.11     234  658.39
   370.6  659.26   419.3  660.12   429.1  660.53   438.8  661.15   458.4   662.8
   497.4  667.44   516.9  669.51   536.4   670.9   575.4  672.88   604.6  675.14
#Mann= 3 , 0 , 0
       0      .1       0   194.1    .045       0   214.1     .08       0
Bank Sta=194.1,214.1
XS Rating Curve= 0 ,0
Exp/Cntr=0.3,0.1

Type RM Length L Ch R = 1 ,4574.9  ,310.1,305.7,302.4
XS GIS Cut Line= 2
     1670729.895      510908.944     1671043.952       512038.47
#Sta/Elev= 30
       0  884.45     9.8  886.08    19.5  886.24    29.3  884.05    39.1  880.53
    58.6  871.21   117.2  840.53   136.8  831.18   156.3  822.87   185.6  814.05
   205.2  805.85   214.9  800.74   244.2   782.6   263.8   772.3   283.3  763.08
   312.6  750.81   390.8  721.41   547.1  667.25   566.6  661.84   590.3  656.92
   605.7  655.89   610.3  656.08   840.2  666.49   918.4  674.02  1035.6  684.13
  1055.1  687.52  1064.9  690.32    1104  703.55  1152.8  717.98  1172.4  723.12
#Mann= 3 , 0 , 0
       0      .1       0   590.3    .045       0   610.3     .08       0
Bank Sta=590.3,610.3
XS Rating Curve= 0 ,0
Exp/Cntr=0.3,0.1

Type RM Length L Ch R = 1 ,4269.1  ,299.6,296.8,292.3
XS GIS Cut Line= 2
     1670541.587      511348.384     1670674.033      511758.516
#Sta/Elev= 27
       0  722.82     9.8  719.48    19.6  715.82    29.4  711.79      49  702.89
    58.8  698.52    68.6  694.31    88.2  686.19      98  681.74   107.8  675.22
   117.5  667.46   127.3  662.19   137.1  660.54   146.9   659.2   156.7   657.7
   166.5  656.66   176.3  656.14   182.5  655.98   186.1  655.88   195.9   655.8
   202.5  655.91   205.7  655.97   215.5  656.58   235.1  658.36   274.3  660.88
   352.6  666.26     431  671.36
#Mann= 3 , 0 , 0
       0      .1       0   182.5    .045       0   202.5     .08       0
Bank Sta=182.5,202.5
XS Rating Curve= 0 ,0
Exp/Cntr=0.3,0.1

Type RM Length L Ch R = 1 ,3972.3  ,252,254.8,258
XS GIS Cut Line= 2
     1670278.327      511491.732     1670520.718      511888.107
#Sta/Elev= 16
       0  690.88    19.4  686.18    67.8   674.2   106.5  664.72   116.2  662.56
   125.8  660.82   135.5   659.7   154.9  657.97   174.2  656.59   192.5  655.03
   193.6  654.93   203.3  654.66   212.5   655.1   232.3  656.55   445.3  669.28
   464.6  670.51
#Mann= 3 , 0 , 0
       0      .1       0   192.5    .045       0   212.5     .08       0
Bank Sta=192.5,212.5
XS Rating Curve= 0 ,0
Exp/Cntr=0.3,0.1

Type RM Length L Ch R = 1 ,3717.5  ,223.1,225.6,227.2
XS GIS Cut Line= 2
     1670102.267      511608.958     1670299.258      512025.495
#Sta/Elev= 28
       0  686.96     9.8  683.12    19.6  679.61    29.4   676.7    39.2  674.46
      49  672.94    68.6   670.2      98  665.86   107.8  664.54   127.4  661.73
   137.2  660.54   156.9  658.34   176.5  655.78   186.3  654.61   196.1  654.12
   205.9  654.11   217.6654.2321   274.5  656.22   294.1  657.03   313.7  658.04
   333.3  659.19   352.9  660.54   382.3  663.18   421.6  667.08   431.4  668.22
   441.2  670.27     451  673.39   460.8   677.2
#Mann= 3 , 0 , 0
       0      .1       0   186.3    .045       0   217.6     .08       0
Bank Sta=186.3,217.6
XS Rating Curve= 0 ,0
Exp/Cntr=0.3,0.1

Type RM Length L Ch R = 1 ,3491.9  ,273.4,273.1,273.1
XS GIS Cut Line= 2
     1669916.202      511650.226     1670102.601      512156.662
#Sta/Elev= 30
       0   703.9    29.4  690.48    39.2  686.14    49.1  681.99    58.9  678.07
    68.7  674.41    78.5  671.19    88.3  668.42   107.9  663.16   117.7  660.92
   127.6  659.31     157   655.7   166.8  654.63   176.6  654.16   186.4   654.1
   197.2  654.12     206  654.17   225.7  654.53   255.1  655.32   274.7  656.05
   294.4  657.18   323.8  659.36   333.6  659.94   421.9  663.67   451.3  665.29
     471  666.74   490.6  668.47   500.4  669.61     520  672.33   539.6  674.77
#Mann= 3 , 0 , 0
       0      .1       0   166.8    .045       0   197.2     .06       0
Bank Sta=166.8,197.2
XS Rating Curve= 0 ,0
Exp/Cntr=0.3,0.1

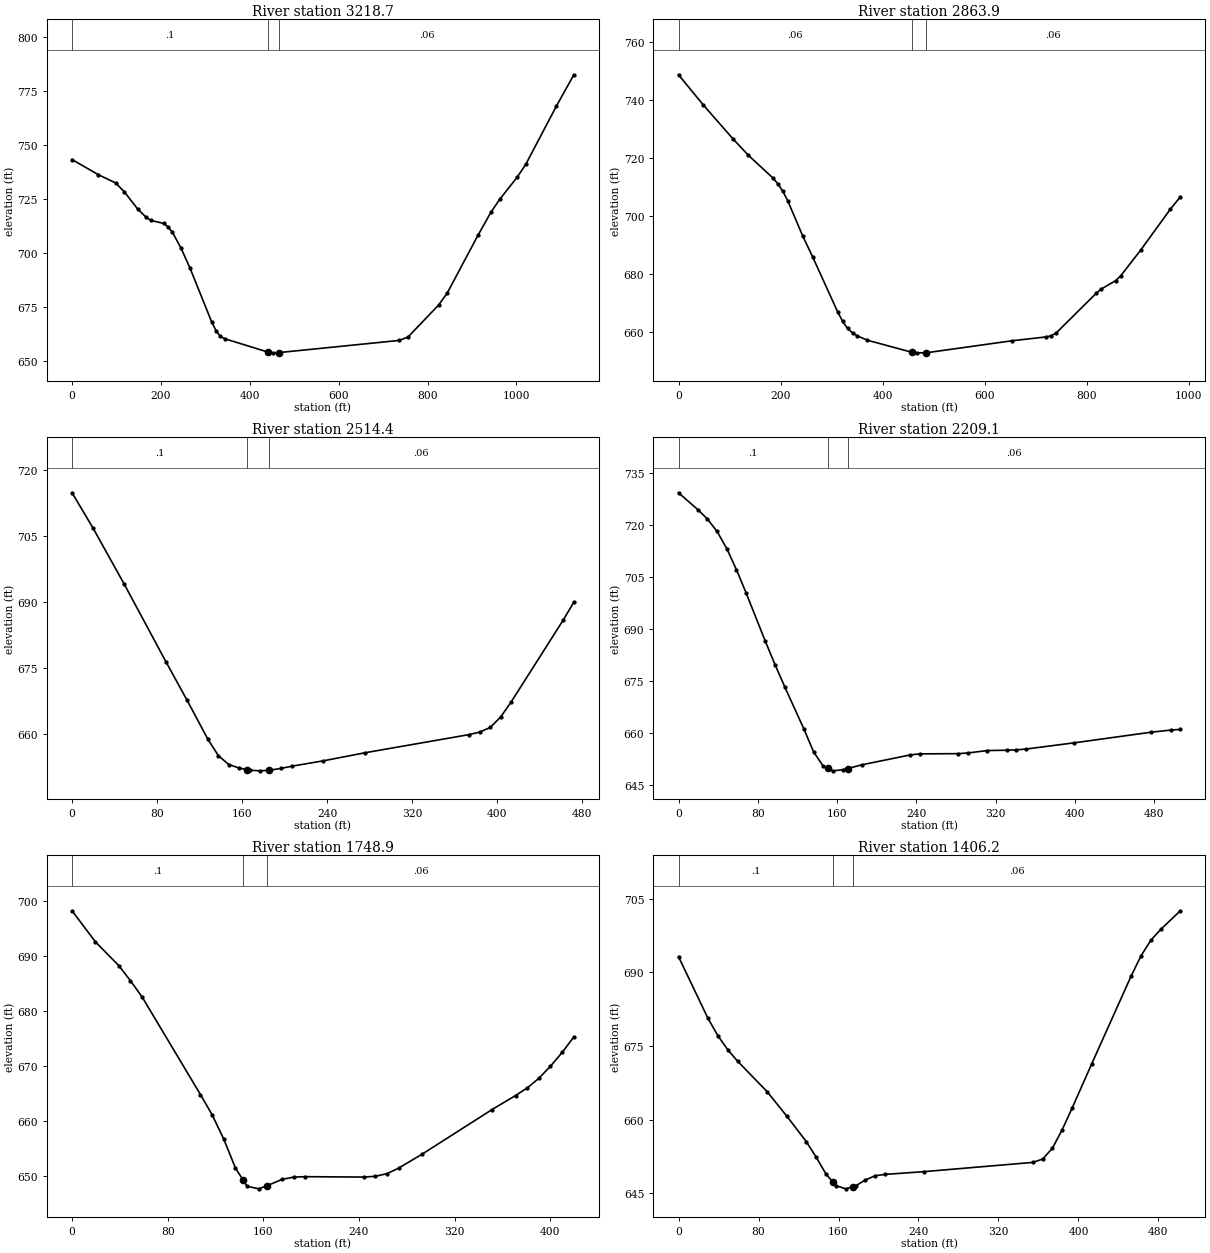
Type RM Length L Ch R = 1 ,3218.7  ,365.1,354.9,344.2
XS GIS Cut Line= 2
     1669555.925      511464.286     1669952.721      512521.321
#Sta/Elev= 30
       0   743.3    58.9  736.32    98.2  732.46   117.8  728.31   147.3   720.5
   166.9  716.54   176.7  715.16   206.2  713.73     216  712.06   225.8  709.65
   245.4   702.2   265.1   693.2   314.2  668.13     324  664.05   333.8  661.44
   343.6  660.36   441.8  654.12   451.6  653.84   465.5  653.96   736.3  659.59
     756  661.19   824.7  675.95   844.3  681.55   913.1  708.16   942.5   718.9
   962.2  724.89  1001.4  735.09  1021.1  741.16  1089.8  768.05  1129.1  782.54
#Mann= 3 , 0 , 0
       0      .1       0   441.8    .045       0   465.5     .06       0
Bank Sta=441.8,465.5
XS Rating Curve= 0 ,0
Exp/Cntr=0.3,0.1

Type RM Length L Ch R = 1 ,2863.9  ,348.7,349.4,349.9
XS GIS Cut Line= 4
     1669065.767      511692.301     1669501.549      512151.499
      1669556.24      512307.788     1669694.286       512430.22
#Sta/Elev= 30
       0  748.58    48.7  738.17   107.1  726.47   136.4  720.98     185  713.09
   194.8  711.06   204.5  708.49   214.3  705.15   243.5   693.1     263   685.9
   311.7   667.1   321.4  663.89   331.1  661.38   340.9  659.84   350.6  658.83
   370.1  657.33   457.8  653.17   467.5     653   485.7  653.03   652.5  657.13
   720.7  658.48   730.5  658.87   740.2  659.88   818.1  673.42   827.8  674.88
   856.9  677.86   866.6  679.51   905.5  688.32   963.7  702.39   983.2  706.61
#Mann= 3 , 0 , 0
       0     .06       0   457.8    .045       0   485.7     .06       0
Bank Sta=457.8,485.7
XS Rating Curve= 0 ,0
Exp/Cntr=0.3,0.1

Type RM Length L Ch R = 1 ,2514.4  ,305.2,305.4,304.9
XS GIS Cut Line= 2
     1669044.176      512165.139     1669366.785      512509.855
#Sta/Elev= 24
       0   714.9    19.7  706.86    49.2  694.02    88.5   676.3   108.2  667.61
   127.9  658.67   137.7  654.96   147.5  652.95   157.4  652.15     165  651.78
   167.2  651.67     177  651.52     185  651.64   196.7  652.07   206.6  652.57
   236.1  653.79   275.4  655.63   373.8  659.79   383.6  660.36   393.4   661.4
   403.3  663.81   413.1  667.22   462.3  685.97   472.1  689.98
#Mann= 3 , 0 , 0
       0      .1       0     165    .045       0     185     .06       0
Bank Sta=165,185
XS Rating Curve= 0 ,0
Exp/Cntr=0.3,0.1

Type RM Length L Ch R = 1 ,2209.1  ,452.7,460.2,465.7
XS GIS Cut Line= 2
     1668831.032      512349.312     1669177.862      512718.023
#Sta/Elev= 30
       0  729.23    19.5  724.38    29.2  721.66    38.9  718.09    48.7  713.14
    58.4  707.11    68.1  700.45    87.6  686.46    97.4  679.73   107.1   673.4
   126.6  661.16   136.3  654.61     146  650.53   150.5  649.91   155.8  649.19
   165.5   649.5   170.5  649.83     185  650.93   233.6  653.76   243.4  654.07
   282.3  654.14     292  654.34   311.5  655.03     331  655.12   340.7  655.23
   350.4  655.46   399.1  657.25     477  660.32   496.5  660.92   506.2  661.11
#Mann= 3 , 0 , 0
       0      .1       0   150.5    .045       0   170.5     .06       0
Bank Sta=150.5,170.5
XS Rating Curve= 0 ,0
Exp/Cntr=0.3,0.1

Type RM Length L Ch R = 1 ,1748.9  ,337.5,342.6,347.9
XS GIS Cut Line= 2
     1668573.541      512639.581     1668777.042      513006.727
#Sta/Elev= 28
       0  698.23    19.5  692.59      39  688.28    48.8  685.53    58.6  682.56
   107.4  664.82   117.2  661.14   126.9  656.72   136.7  651.45   143.3   649.2
   146.4  648.15   156.2  647.68   163.3  648.27   175.7   649.4   185.5  649.82
   195.2  649.89     244  649.82   253.8  649.96   263.6  650.45   273.3  651.46
   292.9  653.99   351.4   662.1     371  664.64   380.7     666   390.5  667.77
   400.2  669.96     410  672.48   419.8   675.3
#Mann= 3 , 0 , 0
       0      .1       0   143.3    .045       0   163.3     .06       0
Bank Sta=143.3,163.3
XS Rating Curve= 0 ,0
Exp/Cntr=0.3,0.1

Type RM Length L Ch R = 1 ,1406.2  ,362.1,365.8,369.2
XS GIS Cut Line= 2
     1668291.781      512730.592     1668434.927      513211.657
#Sta/Elev= 30
       0  693.18    29.5   680.6    39.4  677.09    49.2  674.25      59  671.92
    88.6  665.71   108.3  660.72   127.9   655.5   137.8  652.33   147.6  648.89
   154.7  647.22   157.5  646.56   167.3  645.92   174.7  646.38   177.2  646.54
     187  647.74   196.8   648.6   206.7  648.86     246  649.43   354.3   651.3
   364.1  651.97     374   654.2   383.8  657.98   393.7  662.37   413.3  671.38
   452.7  689.24   462.6  693.36   472.4  696.53   482.2  698.72   501.9  702.53
#Mann= 3 , 0 , 0
       0      .1       0   154.7    .045       0   174.7     .06       0
Bank Sta=154.7,174.7
XS Rating Curve= 0 ,0
Exp/Cntr=0.3,0.1

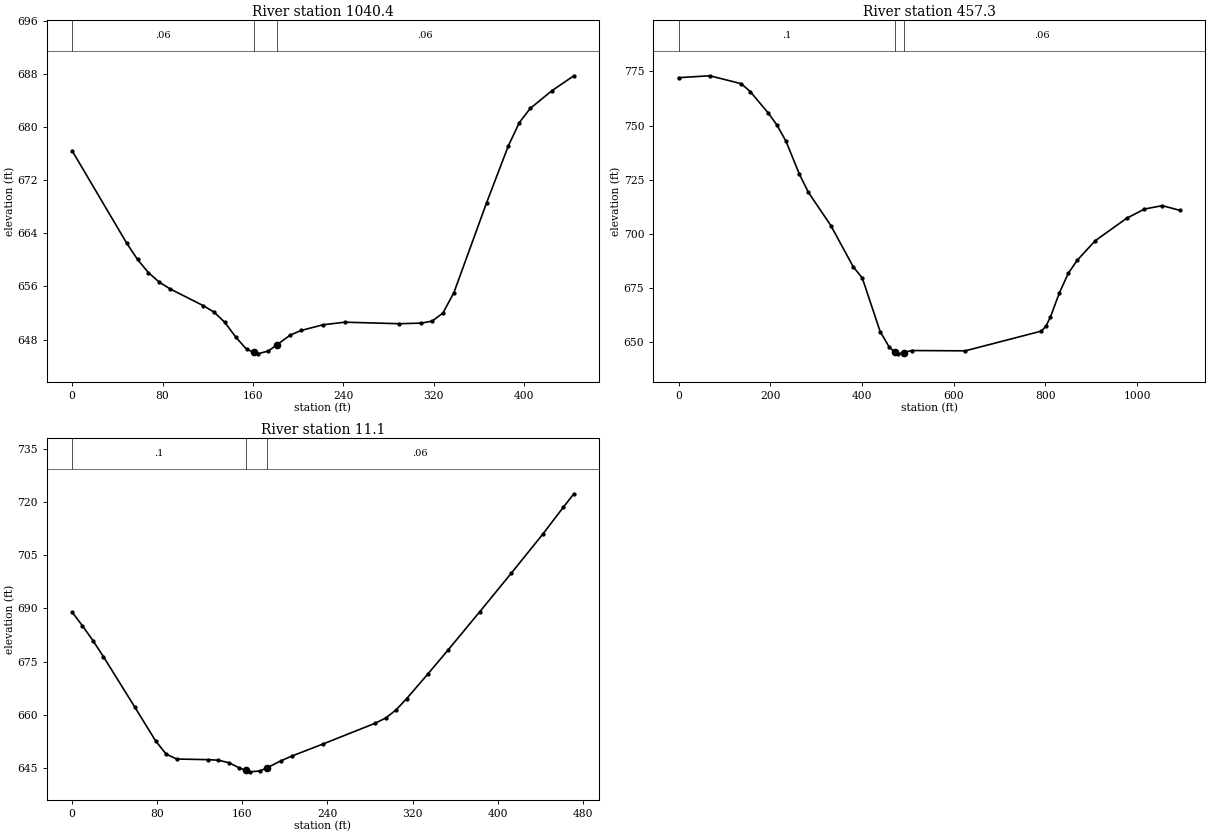
Type RM Length L Ch R = 1 ,1040.4  ,592.7,583,573.2
XS GIS Cut Line= 2
     1667974.995       512809.28     1668037.678      513248.764
#Sta/Elev= 30
       0  676.43    48.2  662.55    57.9  660.06    67.6  658.07    77.2  656.65
    86.9  655.62   115.8  653.14   125.5  652.16   135.1  650.61   144.8  648.39
   154.4  646.56   160.9646.0975   164.1  645.87   173.7   646.3   180.9647.1909
     193  648.69   202.7  649.39     222  650.24   241.3  650.63   289.5   650.4
   308.8  650.49   318.5  650.79   328.1  652.01   337.8  655.08   366.7  668.59
     386  677.17   395.7  680.66   405.3  682.78   424.6  685.46   443.9  687.69
#Mann= 3 , 0 , 0
       0     .06       0   160.9    .045       0   180.9     .06       0
Bank Sta=160.9,180.9
XS Rating Curve= 0 ,0
Exp/Cntr=0.3,0.1

Type RM Length L Ch R = 1 ,457.3   ,439.9,446.2,448.6
XS GIS Cut Line= 2
     1667218.494      512742.756     1667839.007      513644.205
#Sta/Elev= 30
       0  772.09    68.4  772.96   136.8   769.3   156.3  765.68   195.4  755.86
     215  750.08   234.5  742.66   263.8  727.42   283.4  719.08   332.2  703.81
   381.1  684.73   400.6  679.68   439.7  654.88   459.2  647.81   471.4  645.34
   478.8  644.58   491.4  645.16   508.1  646.11   625.4  645.97   791.5  655.09
   801.2  657.31     811  661.51   830.6  672.72   850.1  681.78   869.6  687.81
   908.7  696.79   977.1  707.14  1016.2  711.44  1055.3     713  1094.4  710.76
#Mann= 3 , 0 , 0
       0      .1       0   471.4    .045       0   491.4     .06       0
Bank Sta=471.4,491.4
XS Rating Curve= 0 ,0
Exp/Cntr=0.3,0.1

Type RM Length L Ch R = 1 ,11.1    ,20.2,11.1,2.1
XS GIS Cut Line= 2
      1667138.99      513267.446     1667290.188      513714.077
#Sta/Elev= 30
       0  688.95     9.8  685.08    19.6  680.92    29.5  676.36    58.9  662.16
    78.6  652.55    88.4  648.87    98.2  647.48   127.7   647.3   137.5  647.14
   147.4  646.43   157.2  644.97     163  644.31     167  643.86   176.8  644.12
     183  644.98   196.5     647   206.3  648.29   235.8  651.72   284.9  657.59
   294.7  659.05   304.5  661.35   314.4  664.53     334  671.37   353.6  678.36
   383.1  689.06   412.6  699.89   442.1  710.88   461.7  718.59   471.5  722.35
#Mann= 3 , 0 , 0
       0      .1       0     163    .045       0     183     .06       0
Bank Sta=163,183
XS Rating Curve= 0 ,0
Exp/Cntr=0.3,0.1

Chan Stop Cuts=-1
Use User Specified Reach Order=0
Composite Channel Slope=5